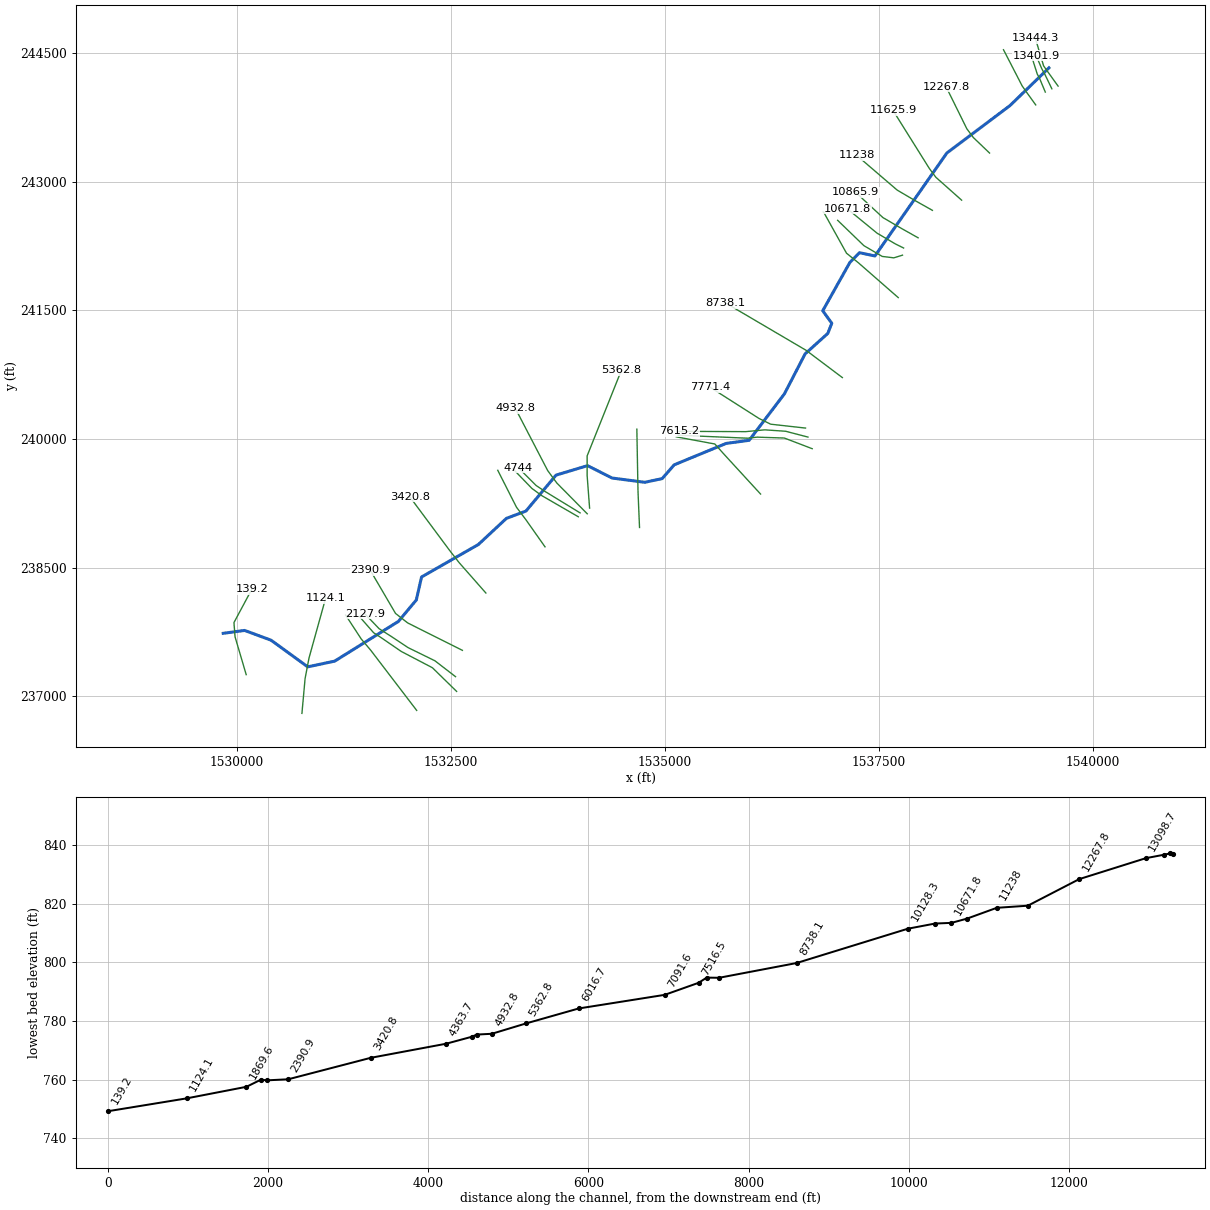
--- CHVXDFRRN.prj (project) ---

Proj Title=CHVXDFRRN
Current Plan=p01
Default Exp/Contr=0,0
English Units
Geom File=g01
Flow File=f01
Plan File=p01
BEGIN DESCRIPTION:
END DESCRIPTION:
DSS Export Rating Curves= 0
DSS Export Rating Curve Sorted= 0
DSS Export Volume Flow Curves= 0
DXF OffsetX= 0
DXF OffsetY= 0
DXF ScaleX= 0
DXF ScaleY= 0

--- CHVXDFRRN.p01 (plan) ---

Plan Title=Floodplain
Program Version=4.00
Geom File=g01
Flow File=f01
K Sum by GR=0
Std Step Tol=0.01
Critical Tol=0.01
Num of Std Step Trials=20
Max Error Tol=0.3
Flow Tol Ratio=0.001
Split Flow NTrial=30
Split Flow Tol=0.02
Split Flow Ratio=0.02
Log Output Level=0
Friction Slope Method=1
Unsteady Friction Slope Method=2
Unsteady Bridges Friction Slope Method=1
Global Log Level=0
CheckData=False
Run HTab=0
Run UNet=0
Run PostProcess=0
UNET Theta=0
UNET Theta Warmup=0
UNET ZTol=0
UNET ZSATol=0
UNET MxIter=0
UNET MaxInSteps=0
UNET DtIC=0
UNET DtMin=0
UNET MaxCRTS=0
UNET WFStab=0
UNET SFStab=0
UNET WFX=0
UNET SFX=0
UNET DSS MLevel=0
UNET DZMax Abort=0
UNET Convert EG Bridges=0
UNET Use Existing IB Tables=0
UNET Froude Limit=0
UNET Froude Power=0
Write IC File=0
Echo Input=False
Echo Output=False
Write Detailed=0

--- CHVXDFRRN.f01 (steady flow) ---

Flow Title=NFF Regression Equation
Program Version=4.10
Number of Profiles= 1
Profile Names=P100yr
River Rch & RM=CHVXDFRRN,Main            ,13444.3
890.0189
River Rch & RM=CHVXDFRRN,Main            ,13098.7
 892.756
River Rch & RM=CHVXDFRRN,Main            ,11625.9
 959.415
River Rch & RM=CHVXDFRRN,Main            ,10671.8
1037.812
River Rch & RM=CHVXDFRRN,Main            ,10128.3
  1223.9
River Rch & RM=CHVXDFRRN,Main            ,7771.4
1286.527
River Rch & RM=CHVXDFRRN,Main            ,7091.6
1435.974
River Rch & RM=CHVXDFRRN,Main            ,5362.8
1456.863
River Rch & RM=CHVXDFRRN,Main            ,4932.8
1522.706
River Rch & RM=CHVXDFRRN,Main            ,2390.9
1574.752
River Rch & RM=CHVXDFRRN,Main            ,2048.6
 1858.19
River Rch & RM=CHVXDFRRN,Main            ,139.2
1891.406
Boundary for River Rch & Prof#=CHVXDFRRN,Main            , 1
Up Type= 0
Dn Type= 3
Dn Slope=0.00469
DSS Import GetInterval= 0
DSS Import GetPeak= 0
DSS Import FillOption= 0

--- CHVXDFRRN.g01 (geometry) ---

Geom Title=USGS 10m DEM
Program Version=4.10

River Reach=CHVXDFRRN       ,Main
Reach XY= 30
     1539487.545      244327.488     1539030.916      243886.511
     1538295.133      243335.493     1537454.886      242134.902
     1537274.195      242173.135     1537162.056      242059.252
     1536845.213       241496.31     1536950.644      241350.613
     1536904.612      241232.375     1536639.343      240993.765
     1536397.731      240527.994     1535985.523      239986.145
     1535716.437      239949.557     1535109.464       239700.05
     1534969.633      239539.552     1534766.148      239496.491
     1534384.068      239546.226     1534097.326       239690.59
      1533729.69      239580.258     1533378.031       239161.51
     1533148.885      239075.473     1532822.238       238771.45
     1532158.197      238392.538     1532096.798      238124.471
     1531887.974      237874.802     1531143.033      237411.565
     1530828.554      237345.151      1530400.27      237655.721
     1530091.242       237769.61     1529841.172      237736.016

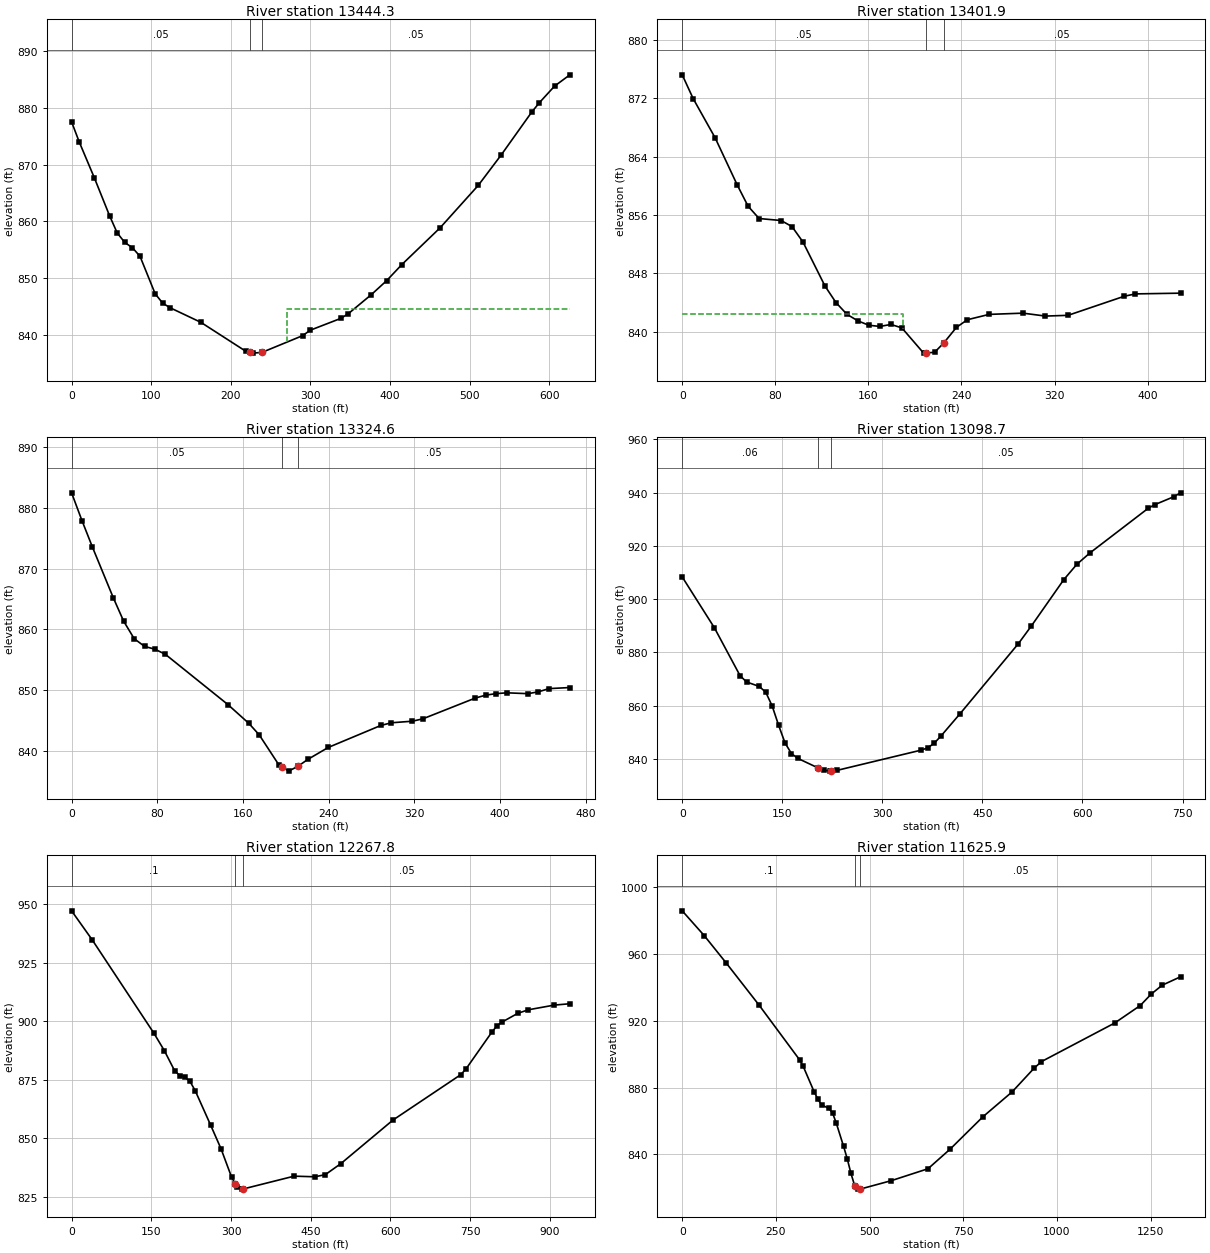
Type RM Length L Ch R = 1 ,13444.3 ,45.1,42.4,39.6
XS GIS Cut Line= 4
     1539594.888      244114.688       1539477.7      244277.448
     1539425.617      244350.365     1539329.263       244671.98
#Sta/Elev= 30
       0  877.57     9.6  874.03    28.6   867.7    47.8  860.99    57.3  857.99
    66.8   856.3    76.4  855.38      86  853.85     105  847.25   114.6  845.58
   124.2  844.76   162.4  842.22   218.5  837.15     224  836.93   227.4  836.79
     239  836.91   290.2  839.87   299.8  840.83   338.1  842.91   347.7  843.75
   376.5   847.1   395.7  849.56   414.9  852.41   462.8  858.87   510.8  866.36
   539.6  871.72   577.9  879.27   587.5  880.93   606.7  883.87   625.9  885.86
#Mann= 3 , 0 , 0
       0     .05       0     224    .045       0     239     .05       0
#XS Ineff= 2 , 0
                           270.4          844.58
Permanent Ineff=
       F       F
Bank Sta=224,239
XS Rating Curve= 0 ,0
Exp/Cntr=0.3,0.1

Type RM Length L Ch R = 1 ,13401.9 ,77.6,77.3,76.9
XS GIS Cut Line= 4
     1539521.971      244083.438     1539443.846      244244.896
     1539403.482      244319.115     1539338.378      244470.157
#Sta/Elev= 30
       0  875.23     9.4  871.97    28.3  866.59    47.2  860.16    56.6  857.22
    66.1  855.53      85  855.26    94.4  854.42   103.8  852.31   122.7  846.28
   132.2     844   141.6   842.4     151   841.5   160.5   840.9   169.9  840.74
   179.4  841.01   188.8  840.54   207.5  837.08   209.8  837.11   216.9  837.19
   224.8  838.47   235.7  840.61   245.1  841.66   263.8  842.39   292.9  842.56
   312.2  842.16   331.6  842.26     380  844.88   389.6   845.2   428.3   845.3
#Mann= 3 , 0 , 0
       0     .05       0   209.8    .045       0   224.8     .05       0
#XS Ineff= 2 , 0
          189.56  842.44
Permanent Ineff=
       F       F
Bank Sta=209.8,224.8
XS Rating Curve= 0 ,0
Exp/Cntr=0.3,0.1

Type RM Length L Ch R = 1 ,13324.6 ,222.9,225.8,228.8
XS GIS Cut Line= 4
     1539445.148      244045.677      1539377.44      244207.136
     1539351.398      244255.313     1539279.784      244479.271
#Sta/Elev= 30
       0   882.5     9.7  877.92    19.4  873.58    38.9  865.21    48.6  861.34
    58.4  858.46    68.1  857.18    77.8  856.72    87.5  855.88   145.9  847.59
   165.4   844.5   175.1   842.6   193.3  837.69   196.1  837.36   202.5  836.62
   211.1   837.4   220.7  838.58   239.6  840.53   288.6  844.15   298.4  844.59
     318  844.85   327.8  845.24   376.8  848.67   386.6  849.15   396.4   849.4
   406.2  849.53   425.8  849.39   435.6  849.69   445.4  850.22     465   850.4
#Mann= 3 , 0 , 0
       0     .05       0   196.1    .045       0   211.1     .05       0
Bank Sta=196.1,211.1
XS Rating Curve= 0 ,0
Exp/Cntr=0.3,0.1

Type RM Length L Ch R = 1 ,13098.7 ,829.8,830.9,831
XS GIS Cut Line= 4
     1539333.169      243895.938     1539231.607      244036.563
     1539175.617       244115.99     1538956.867      244539.167
#Sta/Elev= 30
       0  908.35    48.2  889.28    86.7   871.3    96.4  868.93   115.6  867.24
   125.3  865.04   134.9  859.87   144.6  852.59   154.2  845.98   163.8  842.03
   173.5  840.21   203.6  836.66   212.3  835.79     222  835.45  223.68835.4963
   231.8  835.72   358.1  843.33   367.9  844.17   377.6   845.9   387.3  848.46
   416.5     857     504  883.33   523.4  889.95     572  907.33   591.5  913.07
   610.9  917.31   698.4   934.1   708.1  935.46   737.3  938.51     747  939.94
#Mann= 3 , 0 , 0
       0     .06       0   203.6    .045       0  223.68     .05       0
Bank Sta=203.6,223.68
XS Rating Curve= 0 ,0
Exp/Cntr=0.3,0.1

Type RM Length L Ch R = 1 ,12267.8 ,641.9,641.9,641.9
XS GIS Cut Line= 4
     1538794.107       243334.74     1538604.871      243515.296
     1538528.482      243617.726     1538285.426      244109.046
#Sta/Elev= 30
       0  947.17    38.8  934.78     155  894.87   174.4  887.52   193.7  878.97
   203.4  876.83   213.1  876.17   222.8   874.3   232.5  870.42   261.6  855.67
   281.2  845.54   300.9  833.53   307.9  830.56   310.7  829.37   320.5  828.32
   322.9  828.39   418.7  833.86   457.8  833.59   477.4   834.5   506.8  839.24
   604.7  857.82   731.9  877.15   741.7  879.52   790.7  895.36   800.4  898.08
   810.2  899.71   839.6   903.4   859.2   904.9   908.1  906.91   937.5  907.49
#Mann= 3 , 0 , 0
       0      .1       0   307.9    .045       0   322.9     .05       0
Bank Sta=307.9,322.9
XS Rating Curve= 0 ,0
Exp/Cntr=0.3,0.1

Type RM Length L Ch R = 1 ,11625.9 ,378.7,387.9,396.8
XS GIS Cut Line= 4
     1538467.544      242785.637     1538167.371      243051.754
     1538090.982      243154.184     1537665.461      243832.512
#Sta/Elev= 30
       0   985.6    58.7  970.79   117.4  954.42   205.5  929.12   313.1  896.58
   322.9  892.62   352.2  877.34     362  873.03   371.8  869.62   391.4   867.5
   401.2  864.76     411  858.78   430.6  844.83   440.5  837.27   450.3  828.62
   460.1   821.4     470  819.26   475.1  819.29   558.2  824.34   655.9  831.45
   714.5  843.07   802.4   862.5   880.5  877.41   939.1  891.56   958.6  895.48
  1153.9  918.52  1222.3     929  1251.6  935.84  1280.8  941.14  1329.7  946.17
#Mann= 3 , 0 , 0
       0      .1       0   460.1    .045       0   475.1     .05       0
Bank Sta=460.1,475.1
XS Rating Curve= 0 ,0
Exp/Cntr=0.3,0.1

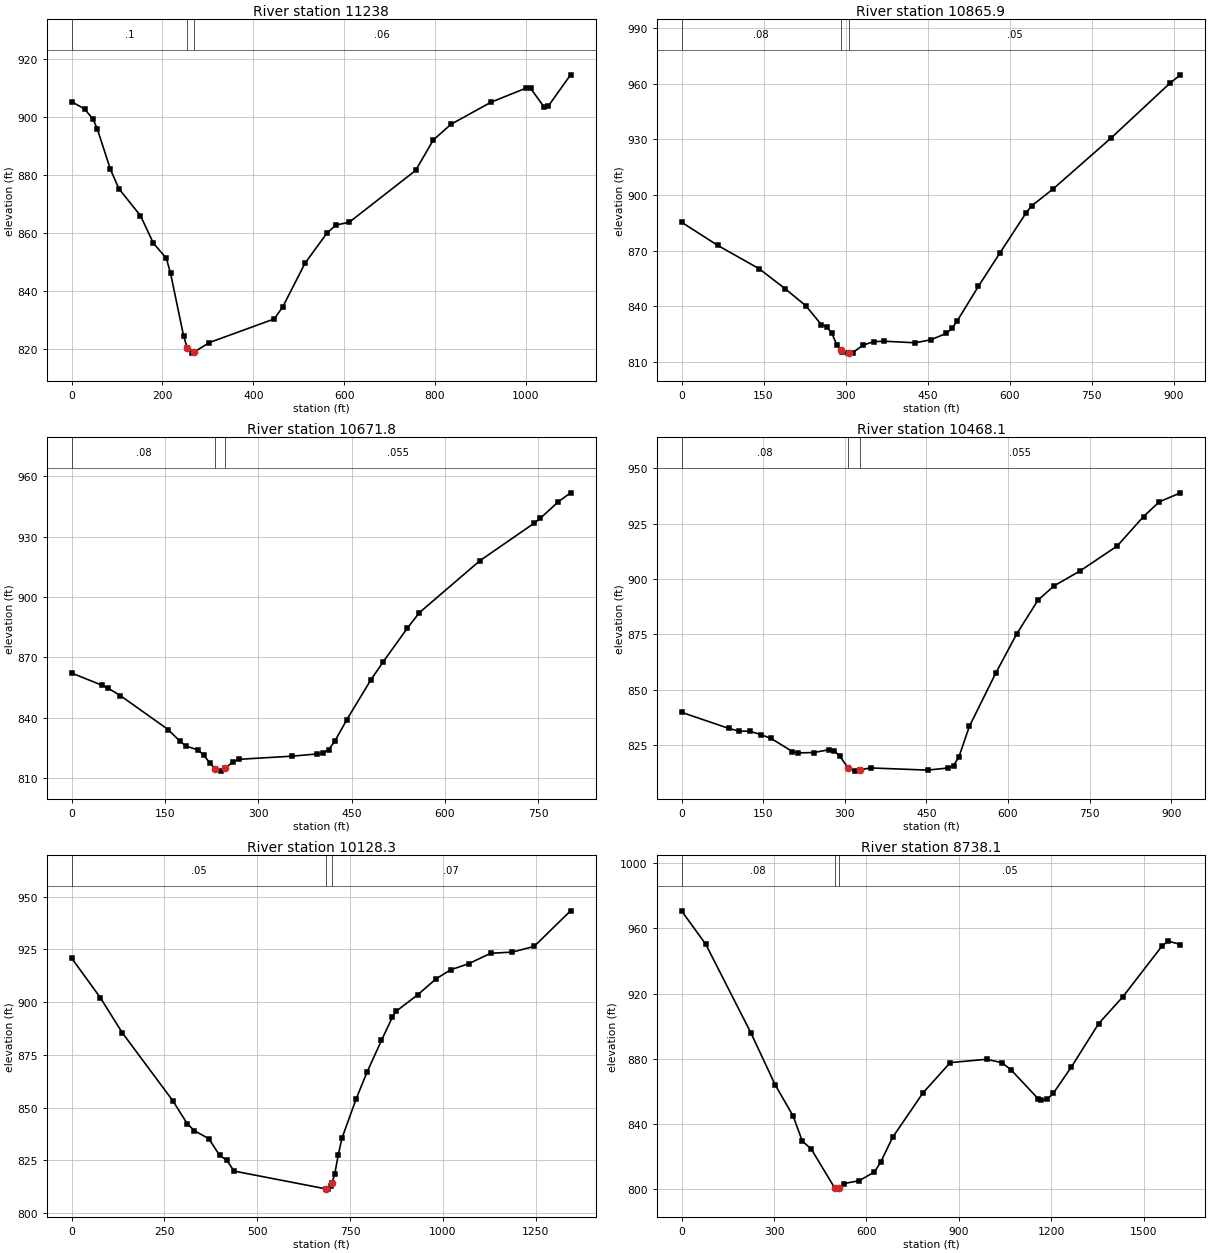
Type RM Length L Ch R = 1 ,11238   ,371.4,372.1,371.5
XS GIS Cut Line= 4
     1538126.398      242666.858     1537928.094      242778.042
     1537714.552      242903.042     1537240.594      243308.424
#Sta/Elev= 30
       0  905.14    28.4  902.66    47.4  899.06    56.8  895.67    85.3  881.88
   104.2  875.14   151.6  865.89     180  856.41   208.4  851.25   217.9  845.99
   246.4  824.56   254.3  820.44   265.4  818.54   269.3  818.88   303.5   822.2
   446.2  830.32   465.3   834.6   513.8  849.49   562.5  859.95     582  862.67
   611.2  863.62   757.4  881.47   796.4  891.98   835.4  897.38     923  904.94
    1001  909.86  1010.8   909.7    1040  903.35  1049.7  903.68  1098.5   914.4
#Mann= 3 , 0 , 0
       0      .1       0   254.3    .045       0   269.3     .06       0
Bank Sta=254.3,269.3
XS Rating Curve= 0 ,0
Exp/Cntr=0.3,0.1

Type RM Length L Ch R = 1 ,10865.9 ,194.2,194.1,194
XS GIS Cut Line= 4
     1537959.732      242346.546     1537761.427      242457.729
     1537547.885      242582.729     1537226.343      242879.387
#Sta/Elev= 30
       0  885.41    66.3  872.91   142.1   860.3   189.5  849.56   227.4  840.34
   255.9  830.15   265.4  829.18   274.9  825.46   284.4  819.16   291.1  816.46
     294  815.29   303.5  814.85   306.1  814.93     313  815.15     332  819.17
   351.1  820.99   370.1  821.28   427.2  820.42   455.8  822.03   484.5  825.54
   494.2  828.15     504  832.17   542.8  850.82   581.7  868.64   630.3  890.53
   640.1  894.18   678.9  903.21   785.9  930.93   892.8  960.27   912.3  964.85
#Mann= 3 , 0 , 0
       0     .08       0   291.1    .045       0   306.1     .05       0
Bank Sta=291.1,306.1
XS Rating Curve= 0 ,0
Exp/Cntr=0.3,0.1

Type RM Length L Ch R = 1 ,10671.8 ,203.8,203.8,203.8
XS GIS Cut Line= 4
     1537790.073      242227.694     1537693.719      242275.437
     1537480.177      242400.437     1537133.823      242683.424
#Sta/Elev= 30
       0  862.15    48.9  856.08    58.6  854.64    78.2  850.98   155.1  834.08
   174.2  828.29   183.7  825.89   202.7  823.99   212.2  821.51   221.7  817.67
   231.2  814.42   240.8  813.41   247.2  814.89   259.8  818.14   269.3  819.28
     355  820.86   393.9  821.93   403.6  822.26   413.3  824.14     423  828.21
   442.5     839   481.4   858.9   500.8  867.66   539.7  884.43   559.2  892.19
   656.4  917.98   743.9  936.67   753.6  939.08   782.8  947.35   802.2  951.72
#Mann= 3 , 0 , 0
       0     .08       0   231.2    .045       0   247.2    .055       0
Bank Sta=231.2,247.2
XS Rating Curve= 0 ,0
Exp/Cntr=0.3,0.1

Type RM Length L Ch R = 1 ,10468.1 ,343.5,339.8,335.8
XS GIS Cut Line= 5
     1537777.052      242144.361     1537675.489      242113.111
     1537540.073      242129.604     1537326.531      242254.604
     1537019.239      242550.611
#Sta/Elev= 30
       0  839.77    86.9  832.48   106.3  831.24   125.8  831.22   145.2  829.73
   164.7  827.95   203.7  822.04   213.4  821.42   242.7  821.58   271.2  822.84
   280.8  822.24   290.3  820.12   306.7  814.48   318.8  813.18   328.3   813.8
   347.4  814.62     452  813.64   490.1  814.61   499.8  815.72   509.5  819.49
   528.9  833.39   577.4  857.49   616.2  875.34     655  890.45   684.1  896.86
   732.5  903.71   800.4  914.91   848.9  928.24     878  934.93   916.8  938.98
#Mann= 3 , 0 , 0
       0     .08       0   306.7    .045       0   328.3    .055       0
Bank Sta=306.7,328.3
XS Rating Curve= 0 ,0
Exp/Cntr=0.3,0.1

Type RM Length L Ch R = 1 ,10128.3 ,1386.5,1390.2,1390.3
XS GIS Cut Line= 4
     1537727.266      241649.497     1537265.461      242052.275
       1537123.1      242166.858     1536855.739      242646.025
#Sta/Elev= 30
       0  920.87    77.8  902.04   136.2  885.58   272.3  853.38   311.2  842.51
   330.7  839.09   369.6  835.33   398.8  827.42   418.2  825.06   437.7  819.97
  686.34811.5005   689.7  811.42   699.3  812.77  701.61814.2116     709  818.82
   718.6   827.8   728.2  835.52   766.7  854.21   795.5   866.7   834.7  881.88
   864.1  892.86   873.9  895.64   932.7  903.53   981.7  911.04  1020.9  915.31
  1069.9  918.25  1128.7  923.15  1187.5  923.74  1246.2  926.44  1344.2  943.28
#Mann= 3 , 0 , 0
       0     .05       0  686.34    .045       0  701.61     .07       0
Bank Sta=686.34,701.61
XS Rating Curve= 0 ,0
Exp/Cntr=0.3,0.1

Type RM Length L Ch R = 1 ,8738.1  ,961,966.7,970
XS GIS Cut Line= 4
     1537074.489      240717.205     1536768.933      240946.372
     1536652.614      241034.046     1535711.641      241586.129
#Sta/Elev= 30
       0  970.86    78.4  950.38   225.2  895.75   303.6  863.95   362.4  844.55
   391.7  829.28   420.8  824.38   496.3  800.62   508.2  799.72   511.3  800.28
   527.6  803.16   576.8  804.92   625.9   810.3   645.6  816.15   684.9  831.59
   783.2  858.88   871.6  877.52   989.6  879.57  1038.7  877.52  1068.2  873.22
  1156.6   855.4  1166.5  854.28  1186.1  854.91  1205.8  858.54  1264.8  874.86
  1353.2   901.5  1431.8  918.02  1559.6  949.42  1579.3  952.24  1618.6  950.14
#Mann= 3 , 0 , 0
       0     .08       0   496.3    .045       0   511.3     .05       0
Bank Sta=496.3,511.3
XS Rating Curve= 0 ,0
Exp/Cntr=0.3,0.1

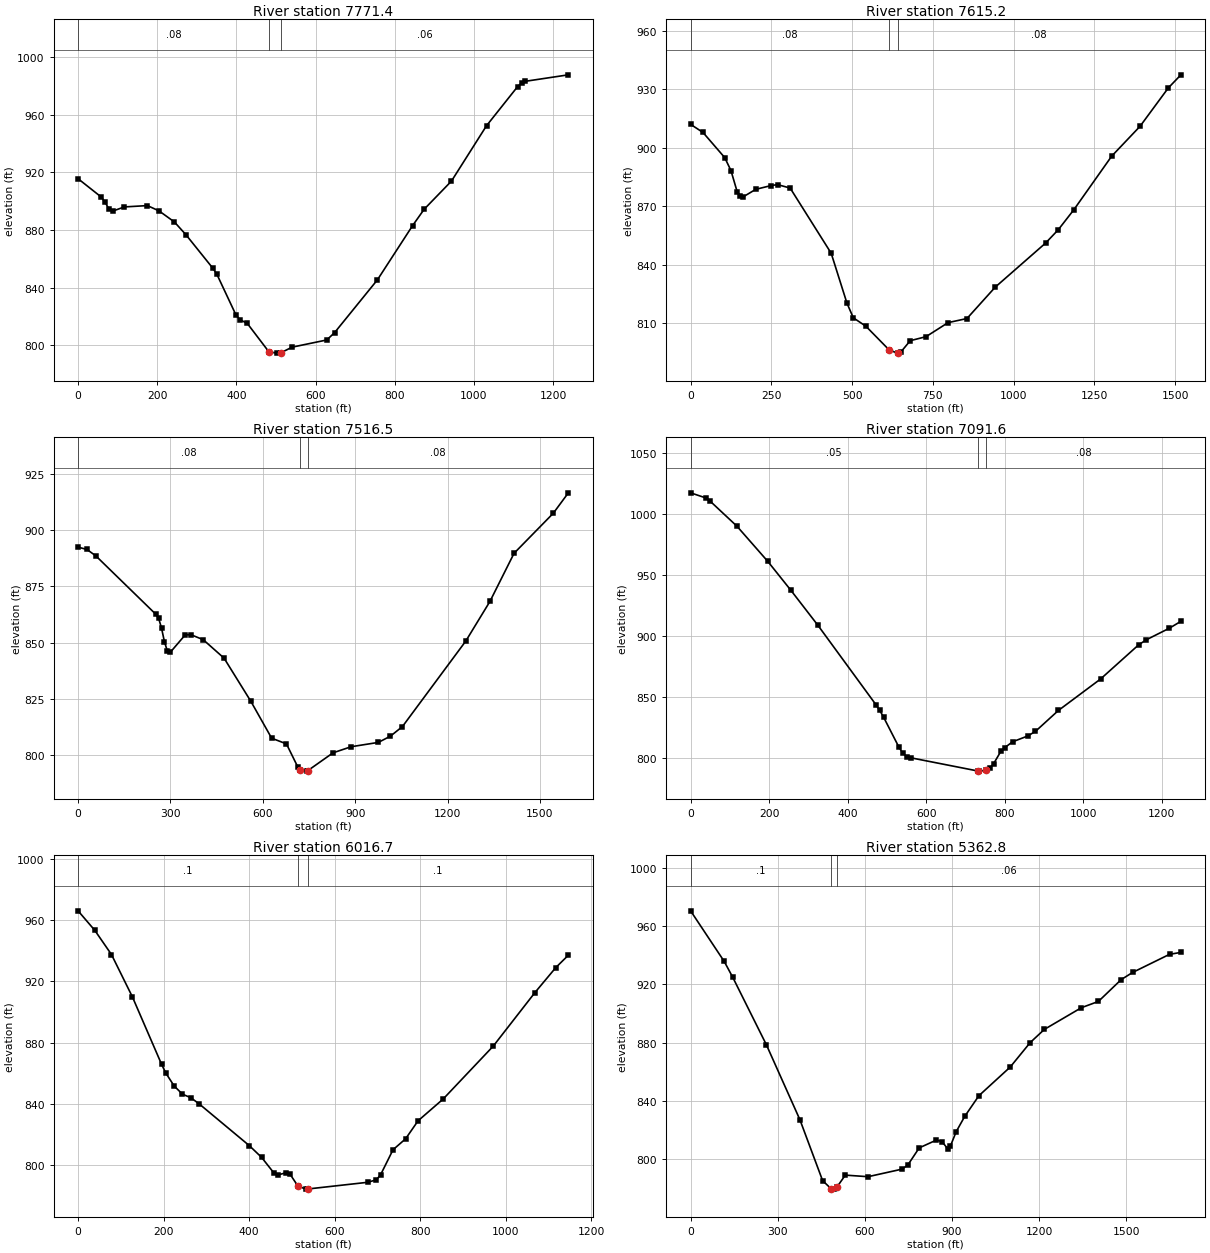
Type RM Length L Ch R = 1 ,7771.4  ,128.1,156.2,174.5
XS GIS Cut Line= 4
     1536643.933      240128.664     1536237.683      240173.802
     1536102.266      240239.775      1535529.35      240604.358
#Sta/Elev= 30
       0  915.65    58.4  902.98    68.1  899.43    77.9  894.66    87.6  893.18
   116.8  896.08   175.2     897   204.4  893.34   243.3  885.67   272.5   876.8
   340.6  853.52   350.4  849.53     399  821.09   408.8  817.94   427.6  815.26
  482.25795.5279   502.9   794.7   512.3  794.96   540.6  798.83   628.3  803.83
     648  808.92   756.2  845.54   844.8  883.03   874.3  894.49   943.2  913.99
  1031.8   952.4  1110.5  979.57  1120.4  982.02  1130.2  983.21  1238.5  987.68
#Mann= 3 , 0 , 0
       0     .08       0  482.25    .045       0   512.3     .06       0
Bank Sta=482.25,512.3
XS Rating Curve= 0 ,0
Exp/Cntr=0.3,0.1

Type RM Length L Ch R = 1 ,7615.2  ,111.6,98.7,96.9
XS GIS Cut Line= 5
     1536672.579      240023.629     1536412.167      240091.412
     1536168.239       240107.83     1535944.107      240086.997
     1535164.766      240090.469
#Sta/Elev= 30
       0  911.94    38.4  907.78   105.7  894.89   124.9  888.28   144.2  877.43
   153.8  875.24   163.4  874.86   201.8  878.65   249.9   880.6   269.1  881.06
   308.2  879.31   435.3   845.9   484.2  820.29   503.8  812.84   542.9   808.5
   615.2  796.31   640.8  794.75   650.6  795.25     680  801.12   728.9  803.18
   797.1  810.37   855.6  812.47   943.2  828.55  1099.1  851.13  1138.1  857.91
  1186.8  868.25  1303.7  895.64  1391.4  910.91    1479  930.59    1518   937.3
#Mann= 3 , 0 , 0
       0     .08       0   615.2    .045       0   640.8     .08       0
Bank Sta=615.2,640.8
XS Rating Curve= 0 ,0
Exp/Cntr=0.3,0.1

Type RM Length L Ch R = 1 ,7516.5  ,447.8,424.9,398.4
XS GIS Cut Line= 5
     1536722.058      239888.212     1536396.566      240012.491
     1536077.787      240022.761     1535966.676      240010.608
      1535154.35       240045.33
#Sta/Elev= 30
       0   892.4      29  891.36    58.1  888.48   251.6  862.73   261.3  860.96
     271  856.51   280.7   850.3   290.3  846.21     300  845.81   348.4  853.52
   367.7  853.48   406.4  851.33   474.1  843.14     561  824.01   628.7  807.61
   676.7  805.09   713.9  794.75  721.46793.6282   741.9     793   745.4  793.15
   828.1  801.13   886.9  803.83     975  805.74  1014.2   808.5  1053.4  812.78
  1259.1  850.72  1337.5   868.3  1415.9  889.68  1543.2  907.43  1592.2   916.5
#Mann= 3 , 0 , 0
       0     .08       0  721.46    .045       0   745.4     .08       0
Bank Sta=721.46,745.4
XS Rating Curve= 0 ,0
Exp/Cntr=0.3,0.1

Type RM Length L Ch R = 1 ,7091.6  ,1091.2,1074.9,1054.1
XS GIS Cut Line= 4
      1536118.76      239359.566     1535699.489      239815.296
     1535584.905        239942.9     1535134.385      240026.233
#Sta/Elev= 30
       0 1017.07    39.3 1012.83    49.2 1010.42     118  989.72   196.6  960.87
   255.6  937.09   324.4   908.4   471.8  843.47   481.6  838.78   491.5  833.18
   530.8  808.44   540.6  803.57   550.4  800.68   560.3  799.85  731.08789.0286
   733.6  788.88   752.6  789.62   762.2  791.46   771.7  794.88   790.8  805.39
   800.5  808.21     820  812.91     859  817.73   878.5  821.51     937  838.66
  1044.2  864.39  1141.7  892.56  1161.2  896.63  1219.7  906.09  1248.9  911.72
#Mann= 3 , 0 , 0
       0     .05       0  731.08    .045       0   752.6     .08       0
Bank Sta=731.08,752.6
XS Rating Curve= 0 ,0
Exp/Cntr=0.3,0.1

Type RM Length L Ch R = 1 ,6016.7  ,654,653.9,653.4
XS GIS Cut Line= 4
     1534704.697      238969.809     1534687.336      239379.532
     1534683.864      239549.671     1534673.447      240115.643
#Sta/Elev= 30
       0  966.15    39.1   953.4    78.1  937.59   126.9  909.99   195.3   865.8
     205  860.18   224.6  851.68   244.1  846.29   263.6  843.99   283.2  839.95
   400.3  812.68     429  805.02   457.4  794.96   466.8  793.44   485.7  794.92
   495.2  794.18   514.1  786.19     533  784.23  536.56784.3019   677.9  788.72
   697.4  790.36   707.1  793.49   736.4  809.99   765.7   817.1     795  828.92
   853.5   843.1   970.7  877.72  1068.2  912.74    1117  929.08  1146.3  937.15
#Mann= 3 , 0 , 0
       0      .1       0   514.1    .045       0  536.56      .1       0
Bank Sta=514.1,536.56
XS Rating Curve= 0 ,0
Exp/Cntr=0.3,0.1

Type RM Length L Ch R = 1 ,5362.8  ,415.4,430,444
XS GIS Cut Line= 4
     1534121.364      239195.504     1534092.978      239570.938
     1534092.978      239805.313      1534494.02      240805.313
#Sta/Elev= 30
       0  970.66   115.8  935.82   144.8  925.06   260.7  878.61   376.5  826.88
   454.6     785   483.9  779.43   493.7  779.16   503.4  780.45   532.8   788.8
   610.9  787.71   728.4  792.93     748  795.76   787.2  807.54     846  812.88
   865.5   811.9   885.1  807.01   894.9   808.9   914.5  818.68   943.9  829.19
   992.9  843.48  1100.6  863.17  1169.2  879.97  1218.2  889.08  1345.5  903.99
  1404.2  908.31  1482.6  923.32  1521.8  928.24  1649.1  940.72  1688.3  942.06
#Mann= 3 , 0 , 0
       0      .1       0   483.9    .045       0   503.4     .06       0
Bank Sta=483.9,503.4
XS Rating Curve= 0 ,0
Exp/Cntr=0.3,0.1

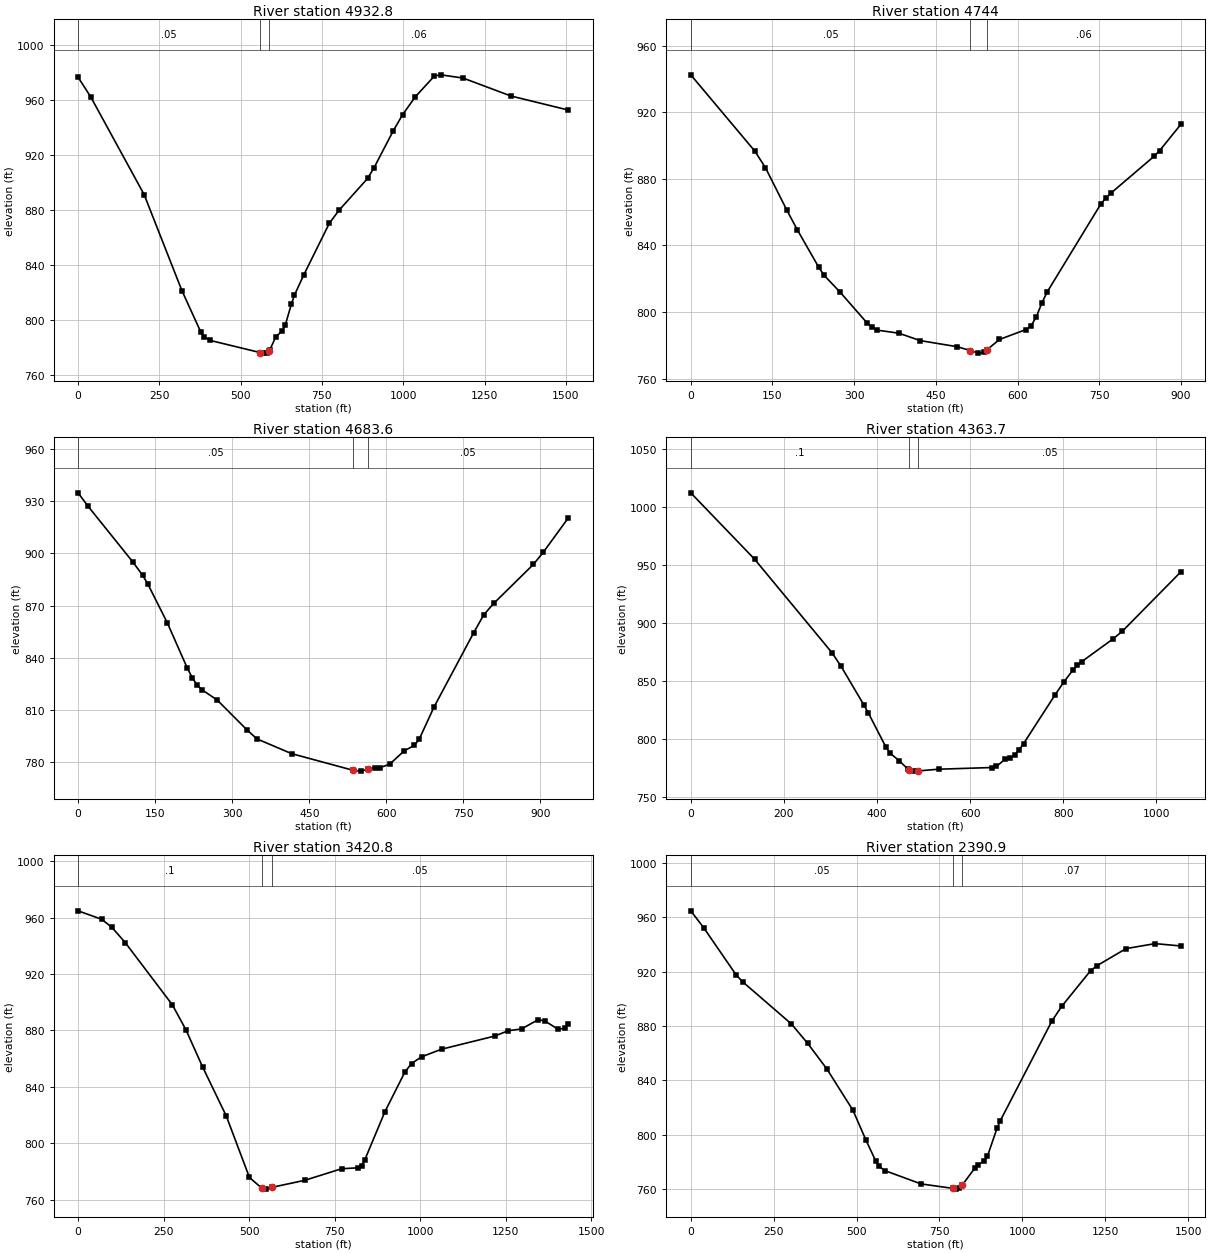
Type RM Length L Ch R = 1 ,4932.8  ,180.7,188.8,196.6
XS GIS Cut Line= 4
     1534093.586      239129.532     1533739.419      239487.171
      1533631.78      239633.004     1533251.832      240362.605
#Sta/Elev= 30
       0  976.66    38.7   962.4   203.3  891.09   319.4  821.12   377.5  790.96
   387.2  787.59   406.5  784.86   560.6  775.98   570.1  775.61   579.6  775.72
   585.9  777.06   589.2  777.76   608.3  787.55   627.4  791.73   636.9  795.83
     656   811.3   665.5  817.91   694.4  832.74   772.7  870.19   802.1  879.58
   890.2  902.85   909.8  910.52   968.6  937.29     998  949.34  1037.1  962.36
  1095.9  977.54  1115.5  978.37    1184  976.01  1330.9  962.96  1507.2  952.72
#Mann= 3 , 0 , 0
       0     .05       0   560.6    .045       0   585.9     .06       0
Bank Sta=560.6,585.9
XS Rating Curve= 0 ,0
Exp/Cntr=0.3,0.1

Type RM Length L Ch R = 1 ,4744    ,61.4,60.5,59.5
XS GIS Cut Line= 4
     1534010.253      239139.948      1533600.53      239389.948
     1533496.364      239459.393      1533288.03      239667.726
#Sta/Elev= 30
       0  942.48   117.5  896.72   137.1  886.71   176.3  861.27   195.9  849.24
   235.1  826.82   244.9  822.05   274.3  811.92   323.2  793.64     333  790.88
   342.8  789.13     382  787.32   421.2  782.88   489.6  779.17   513.3776.8763
   528.1  775.35   537.8  775.88  543.51777.2756   566.6  783.54     615  789.47
   624.8  791.72   634.6  797.31   644.4  805.38   654.3  812.07   752.5  864.75
   762.3  868.66   772.1  871.65   850.7  893.58   860.5  896.88   899.8  912.75
#Mann= 3 , 0 , 0
       0     .05       0   513.3    .045       0  543.51     .06       0
Bank Sta=513.3,543.51
XS Rating Curve= 0 ,0
Exp/Cntr=0.3,0.1

Type RM Length L Ch R = 1 ,4683.6  ,326.6,319.9,313.3
XS GIS Cut Line= 4
     1533989.419      239094.809     1533562.336      239341.337
     1533447.753      239424.671      1533225.53      239653.837
#Sta/Elev= 30
       0  934.95    19.3  927.28   106.4  895.19   125.7  887.46   135.4  882.64
     174  859.89   212.7  833.91   222.4  828.39   232.1  824.04   241.7  821.34
   270.7  815.61   328.8  798.36   348.1  793.18   415.8  784.66  534.95775.1129
   549.8   774.6  564.66775.6945   578.1  776.65   587.6  776.59   606.5  778.59
   634.8  786.27   654.2  789.39   663.8  792.87   692.8  811.51   770.2  854.43
   789.6  864.64   808.9   871.2   886.3  893.72   905.7  900.79     954   920.4
#Mann= 3 , 0 , 0
       0     .05       0  534.95    .045       0  564.66     .05       0
Bank Sta=534.95,564.66
XS Rating Curve= 0 ,0
Exp/Cntr=0.3,0.1

Type RM Length L Ch R = 1 ,4363.7  ,942.2,942.9,942.7
XS GIS Cut Line= 4
      1533600.53      238744.115     1533374.836      239063.559
     1533267.197      239205.921     1533048.447      239636.476
#Sta/Elev= 30
       0 1012.44   136.9  955.24   303.1  874.52   322.7  862.72   371.6  829.45
   381.4  822.37   419.3  792.78   428.7   787.5   447.5  781.22   466.3  774.01
   469.2   773.5   475.7  772.35   485.1  772.23  487.36772.3598     532  773.89
   646.9  775.34   656.5  776.37   675.8  782.76   685.5  783.74   695.2  785.89
   704.8   790.4   714.5  795.89   782.1  837.96   801.4  849.34   820.7  859.53
   830.4  863.67     840  866.85   907.7  886.63     927  893.09  1052.5  944.25
#Mann= 3 , 0 , 0
       0      .1       0   469.2    .045       0  487.36     .05       0
Bank Sta=469.2,487.36
XS Rating Curve= 0 ,0
Exp/Cntr=0.3,0.1

Type RM Length L Ch R = 1 ,3420.8  ,1025.1,1029.9,1031.9
XS GIS Cut Line= 4
     1532909.558      238205.921     1532597.058      238560.087
     1532485.947      238702.448     1532020.669      239327.448
#Sta/Elev= 30
       0  964.86    68.9  958.87    98.4  953.26   137.8  942.35   275.5  898.19
   314.9  880.62   364.1  854.01     433  819.36   500.8  775.67     537  768.08
   548.4  767.42   567.4  768.74   662.6  773.69   769.8  781.87   818.5  782.56
   828.2  784.08     838   788.3   896.4  822.26   954.8  850.44   974.3  856.51
  1003.5  861.27    1062  866.68  1217.8  876.04  1256.8   879.8  1295.7  881.06
  1344.4  887.64  1363.9  886.74  1402.9  880.76  1422.4  881.71  1432.1  884.78
#Mann= 3 , 0 , 0
       0      .1       0     537    .045       0   567.4     .05       0
Bank Sta=537,567.4
XS Rating Curve= 0 ,0
Exp/Cntr=0.3,0.1

Type RM Length L Ch R = 1 ,2390.9  ,261,263,265.4
XS GIS Cut Line= 4
     1532635.253      237537.518     1531996.364      237856.962
     1531854.003      237968.073     1531558.864      238471.546
#Sta/Elev= 30
       0  964.74    39.1  952.31     137  917.58   156.6  912.54   303.3  881.63
   352.3  867.42     411  848.32   489.2   818.1   528.4  796.22   557.7  780.92
   567.5  776.87   587.1  773.58   694.7  763.94   790.3  760.67   799.8  760.11
   809.4  760.62   818.8  763.05   856.9  775.62   866.4  778.19   885.4  780.69
   894.9  784.26   924.1  805.11   933.8  810.45  1089.4  883.74  1118.6  894.41
  1206.1  920.74  1225.6  924.43  1313.1  936.96  1400.7  940.63  1478.5  938.89
#Mann= 3 , 0 , 0
       0     .05       0   790.3    .045       0   818.8     .07       0
Bank Sta=790.3,818.8
XS Rating Curve= 0 ,0
Exp/Cntr=0.3,0.1

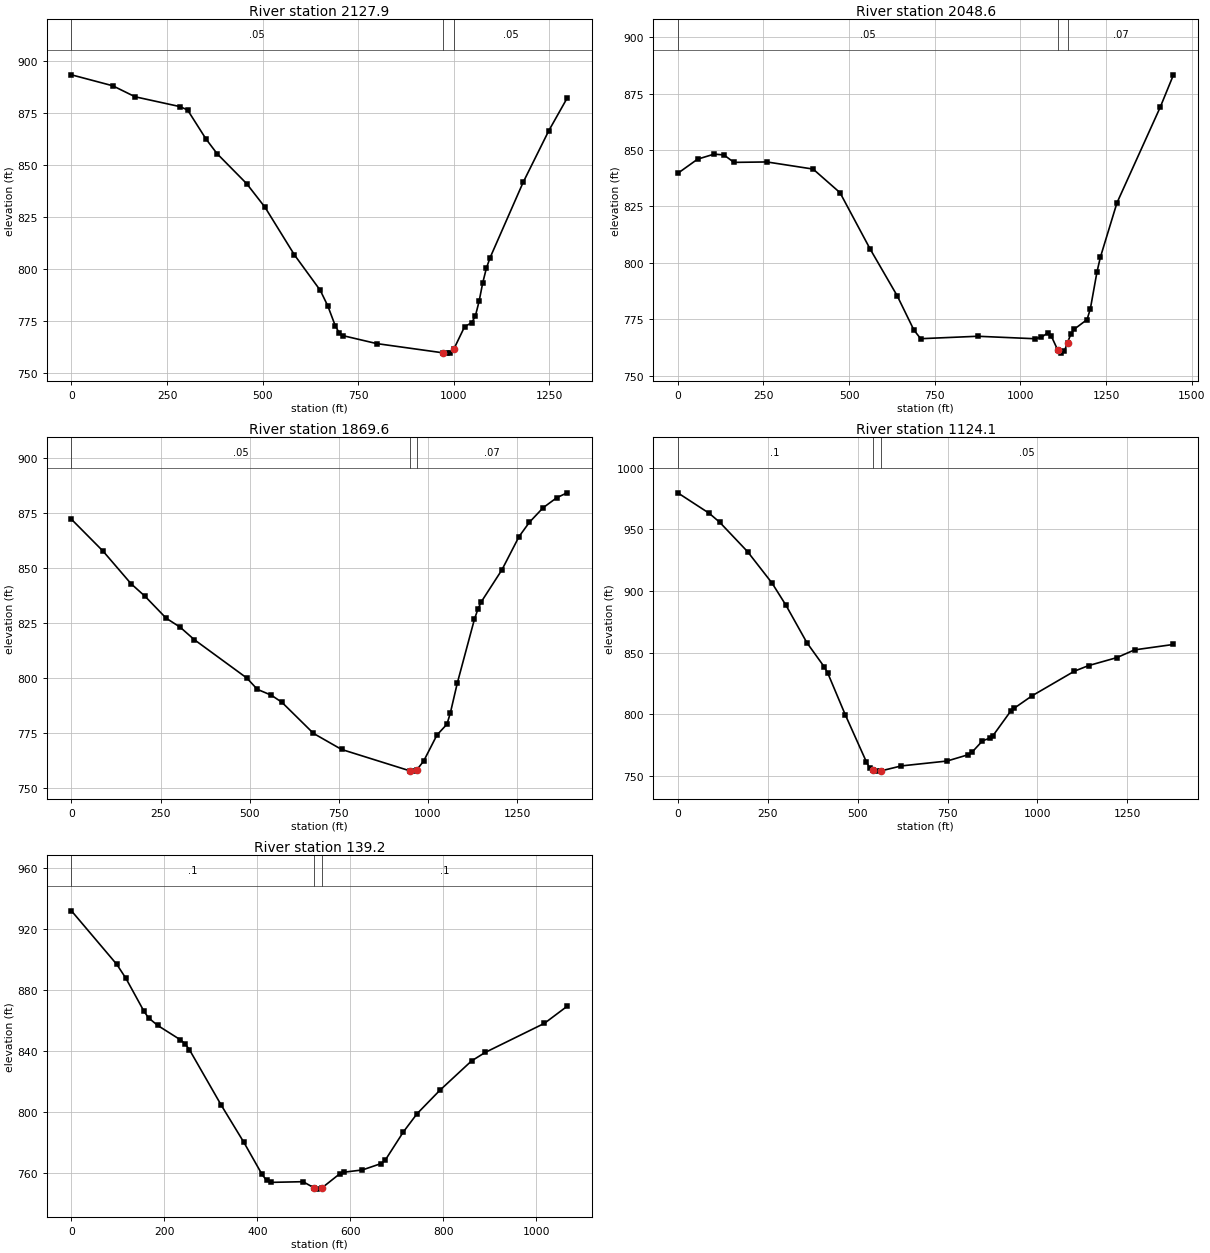
Type RM Length L Ch R = 1 ,2127.9  ,79,79.2,78.7
XS GIS Cut Line= 6
     1532554.957       237230.66     1532314.231      237415.941
      1532002.44      237568.334     1531805.825      237698.542
     1531662.596      237789.688     1531496.364      237962.865
#Sta/Elev= 30
       0  893.53   107.8  888.28   166.6  882.97   284.2  878.24   303.8  876.61
     352  862.65   380.9  855.62     458  841.26   506.2  829.87   583.3  806.94
   650.8  789.91   670.5  782.41   690.1  772.84   699.9   769.6   709.8  768.16
   798.2  764.34   971.5   759.9     981  759.75   990.4  759.92   999.8   761.6
  1028.1  772.41    1047  774.43  1056.4  777.59    1066  784.57  1075.6  793.51
  1085.2   800.6  1094.8   805.6  1181.2   841.8  1248.4  866.67  1296.4  882.34
#Mann= 3 , 0 , 0
       0     .05       0   971.5    .045       0   999.8     .05       0
Bank Sta=971.5,999.8
XS Rating Curve= 0 ,0
Exp/Cntr=0.3,0.1

Type RM Length L Ch R = 1 ,2048.6  ,185.6,179,172
XS GIS Cut Line= 6
     1532567.978      237058.785     1532285.274      237334.646
     1531919.975      237525.365      1531694.28      237679.879
     1531598.794      237742.379     1531432.128      237931.615
#Sta/Elev= 30
       0   839.7    57.8  845.98     106  848.22   134.9  847.86   163.8  844.56
   260.1  844.75     395  841.59   473.5  831.13   561.8  806.05   640.3  785.45
   689.3  770.19     709  766.36   875.5  767.44  1041.5  766.35  1061.1  766.98
  1080.6     769  1090.1  767.58  1109.1  761.33  1118.6  759.96  1128.2  760.72
  1137.7  764.62  1147.2  768.38  1156.7  770.51  1194.7  774.84  1204.4   779.7
  1223.8  796.08  1233.5  802.46    1282  826.62  1408.1  868.98  1446.9  883.39
#Mann= 3 , 0 , 0
       0     .05       0  1109.1    .045       0  1137.7     .07       0
Bank Sta=1109.1,1137.7
XS Rating Curve= 0 ,0
Exp/Cntr=0.3,0.1

Type RM Length L Ch R = 1 ,1869.6  ,765.6,745.5,725.3
XS GIS Cut Line= 4
     1532101.398      236836.997     1531563.204      237540.122
     1531454.697       237668.16     1531270.235      237950.278
#Sta/Elev= 30
       0  872.23    88.6  857.73   167.2  842.88   206.6  837.13   265.6   827.2
     305  823.08   344.4  817.44   491.9  799.94   521.4   794.8   560.8  792.11
   590.3   788.9   678.8  774.74   757.6  767.43   950.7  757.61     960  757.55
   969.4  758.29     988  762.15  1025.3  774.01  1053.3  778.92  1062.9   784.1
  1082.2  797.58  1130.3  826.69    1140  831.27  1149.6  834.65  1207.4   849.2
  1255.5  864.36  1284.4  870.84    1323  877.49  1361.5  882.08  1390.4  884.28
#Mann= 3 , 0 , 0
       0     .05       0   950.7    .045       0   969.4     .07       0
Bank Sta=950.7,969.4
XS Rating Curve= 0 ,0
Exp/Cntr=0.3,0.1

Type RM Length L Ch R = 1 ,1124.1  ,978.1,984.9,989.2
XS GIS Cut Line= 4
     1530760.687      236802.709     1530797.579      237208.525
     1530843.152       237447.24     1531038.464      238148.195
#Sta/Elev= 30
       0  979.76    87.3  963.15   116.4   955.9     194  931.98     262  906.46
   300.8   888.4     359  857.97   407.5  838.23   417.2  833.14   465.8  799.36
   524.1  761.34   533.9  755.87   541.5  754.31   553.3  753.61  564.93753.7971
   621.4  757.84   748.8  761.82   807.8  766.97   817.7  768.86   847.2  778.21
   866.8  780.32   876.7  782.56   925.8  802.42   935.7  804.79   984.8  814.78
  1102.8  834.84  1142.2  839.37  1220.8  845.85    1270  852.14  1378.2  856.55
#Mann= 3 , 0 , 0
       0      .1       0   541.5    .045       0  564.93     .05       0
Bank Sta=541.5,564.93
XS Rating Curve= 0 ,0
Exp/Cntr=0.3,0.1

Type RM Length L Ch R = 1 ,139.2   ,118,139.1,160.7
XS GIS Cut Line= 4
     1530109.645      237254.098     1529979.437      237694.202
     1529966.416      237860.868     1530174.749      238248.889
#Sta/Elev= 30
       0  931.93    97.6  896.75   117.2   887.6   156.2   865.9     166  861.62
   185.5   856.7   234.4  847.26   244.1  844.73   253.9  840.74   322.2  804.39
   371.1  779.88   410.1  758.87   419.9  754.92   429.7  753.66   498.3   754.1
   521.6  750.14   527.8  749.22  539.89750.2404     577  759.22   586.8  760.35
   626.1  761.82   665.3   765.9   675.1   768.2   714.2  786.78   743.6  798.71
   792.5  814.05     861  833.42   890.4  838.98  1017.6  858.05  1066.6  869.26
#Mann= 3 , 0 , 0
       0      .1       0   521.6    .045       0  539.89      .1       0
Bank Sta=521.6,539.89
XS Rating Curve= 0 ,0
Exp/Cntr=0.3,0.1

Chan Stop Cuts=-1
Use User Specified Reach Order=0
Composite Channel Slope=5